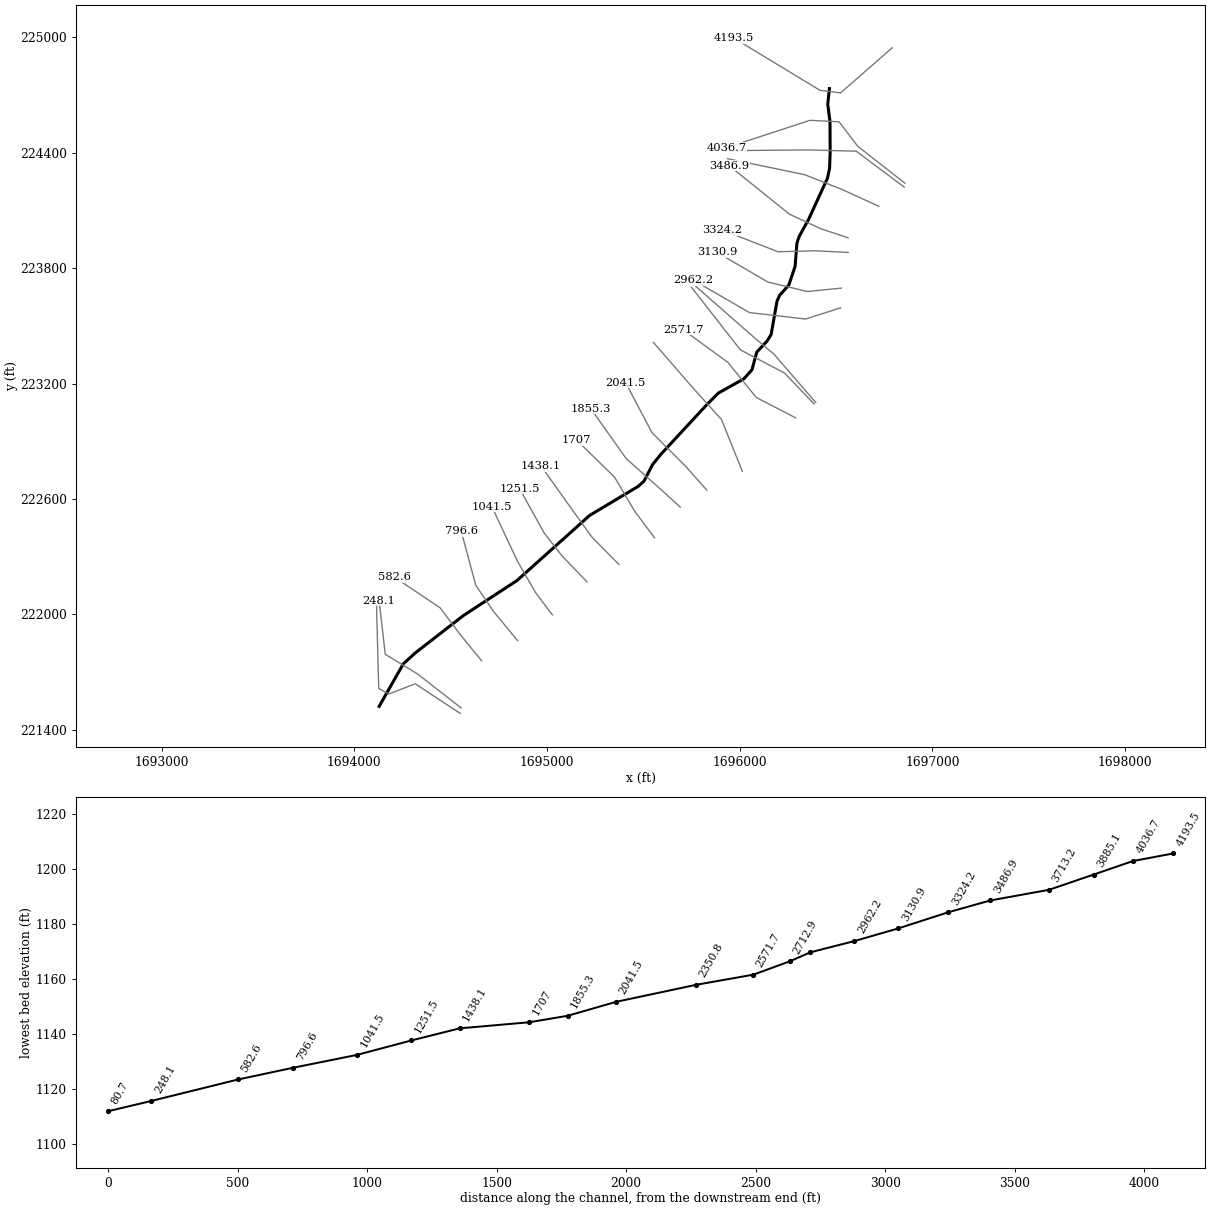
--- bchfrk.prj (project) ---

Proj Title=bchfrk
Current Plan=p01
Default Exp/Contr=0,0
English Units
Geom File=g01
Flow File=f01
Plan File=p01
BEGIN DESCRIPTION:
END DESCRIPTION:
DSS Export Rating Curves= 0
DSS Export Rating Curve Sorted= 0
DSS Export Volume Flow Curves= 0
DXF OffsetX= 0
DXF OffsetY= 0
DXF ScaleX= 0
DXF ScaleY= 0

--- bchfrk.p01 (plan) ---

Plan Title=Approximate Study - 100 yr
Program Version=4.00
Short Identifier=100 yr
Geom File=g01
Flow File=f01
Subcritical Flow
K Sum by GR= 0
Std Step Tol= 0.01
Critical Tol= 0.01
Num of Std Step Trials= 20
Max Error Tol= 0.3
Flow Tol Ratio= 0.001
Split Flow NTrial= 30
Split Flow Tol= 0.02
Split Flow Ratio= 0.02
Log Output Level= 0
Friction Slope Method= 1
Unsteady Friction Slope Method= 2
Unsteady Bridges Friction Slope Method= 1
Parabolic Critical Depth
Global Vel Dist= 0 , 0 , 0
Global Log Level= 0
CheckData=True
Encroach Param=-1 ,0,0, 0
Run HTab= 0
Run UNet= 0
Run PostProcess= 0
Run WQNet= 0
UNET Theta= 0
UNET Theta Warmup= 0
UNET ZTol= 0
UNET ZSATol= 0
UNET MxIter= 0
UNET MaxInSteps= 0
UNET DtIC= 0
UNET DtMin= 0
UNET MaxCRTS= 0
UNET WFStab= 0
UNET SFStab= 0
UNET WFX= 1
UNET SFX= 1
UNET DSS MLevel= 1
UNET DZMax Abort= 0
UNET Convert EG Bridges= 0
UNET Use Existing IB Tables= 0
UNET Froude Reduction=False
UNET Froude Limit= 0
UNET Froude Power= 0
UNET Time Slicing=0,0, 5
Write IC File= 0
Echo Input=False
Echo Output=False
Write Detailed= 0
Detailed Automatic Start=False, 0
WQ ULTIMATE=-1
WQ Max Comp Step=1HOUR
WQ Output Interval=15MIN
WQ Output Selected Increments= 0
WQ Output face flow=0
WQ Output face velocity=0
WQ Output face area=0
WQ Output face dispersion=0
WQ Output cell volume=0
WQ Output cell surface area=0
WQ Output cell continuity=0
WQ Output face conc=0
WQ Output face dconc_dx=0
WQ Output face courant=0
WQ Output face peclet=0
WQ Output face adv mass=0
WQ Output face disp mass=0
WQ Output cell mass=0
WQ Output cell source sink temp=0
WQ Output cell source sink nsm=0
WQ Output MaxMinRange=-1
WQ Daily Max Min Mean=-1
WQ Daily Range=0
WQ Daily Time=0
WQ Create Restart=0
WQ Fixed Restart=0
WQ System Summary=False
Sorting and Armoring Iterations= 10
XS Update Threshold= 0.02
Hydraulics Update Threshold= 0.02
Energy Slope Method= 1
Volume Change Method= 0
XS Weighting Method= 0
Number of US Weighted Cross Sections= 1
Number of DS Weighted Cross Sections= 1
Upstream XS Weight=0.25
Main XS Weight=0.5
Downstream XS Weight=0.25
Number of DS XS's Weighted with US Boundary= 1
Upstream Boundary Weight= 1
Weight of XSs Associated with US Boundary= 0
Number of US XS's Weighted with DS Boundary= 1
Downstream Boundary Weight= 0.5
Weight of XSs Associated with DS Boundary= 0.5
Sediment Output Level= 4
Mass or Volume Output= 0
Output Increment Type= 1
Profile and TS Output Increment= 10
XS Output Flag= 0
XS Output Increment= 10
Disregard all LS=0
Disregard all Conn=0
Disregard all Breaches=0
Disregard all Pumps=0

--- bchfrk.f01 (steady flow) ---

Flow Title=USGS Regression Equation
Program Version=4.00
Number of Profiles= 1
Profile Names=P100yr
River Rch & RM=bchfrk,Main            ,4193.5
     366
River Rch & RM=bchfrk,Main            ,3885.1
     389
River Rch & RM=bchfrk,Main            ,2041.5
     427
River Rch & RM=bchfrk,Main            ,248.1
     467
Boundary for River Rch & Prof#=bchfrk,Main            , 1
Up Type= 0
Dn Type= 3
Dn Slope=0.015
DSS Import GetInterval= 0
DSS Import GetPeak= 0
DSS Import FillOption= 0

--- bchfrk.g01 (geometry) ---

Geom Title=USGS 3m DEM
Program Version=4.00

River Reach=bchfrk          ,Main
Reach XY= 30
     1696465.318      224733.627     1696456.561      224652.306
     1696468.283      224563.061     1696469.208      224400.368
     1696466.001      224318.661     1696455.239      224267.859
     1696357.905      224055.432     1696307.734      223963.885
     1696296.607      223929.752     1696287.333      223810.137
     1696254.924      223712.611     1696206.886      223659.012
     1696193.268      223628.262     1696162.872      223455.087
     1696141.579      223420.684     1696088.211      223363.538
     1696063.536      223272.099     1696021.779       223225.03
     1695889.122      223150.498     1695833.242      223094.721
     1695592.387      222834.126     1695547.828      222779.089
     1695502.863      222692.248     1695472.126      222664.865
     1695221.502      222514.727     1694843.656      222175.504
     1694566.779      221994.237     1694315.689       221798.81
     1694254.239      221742.543     1694128.628      221521.225

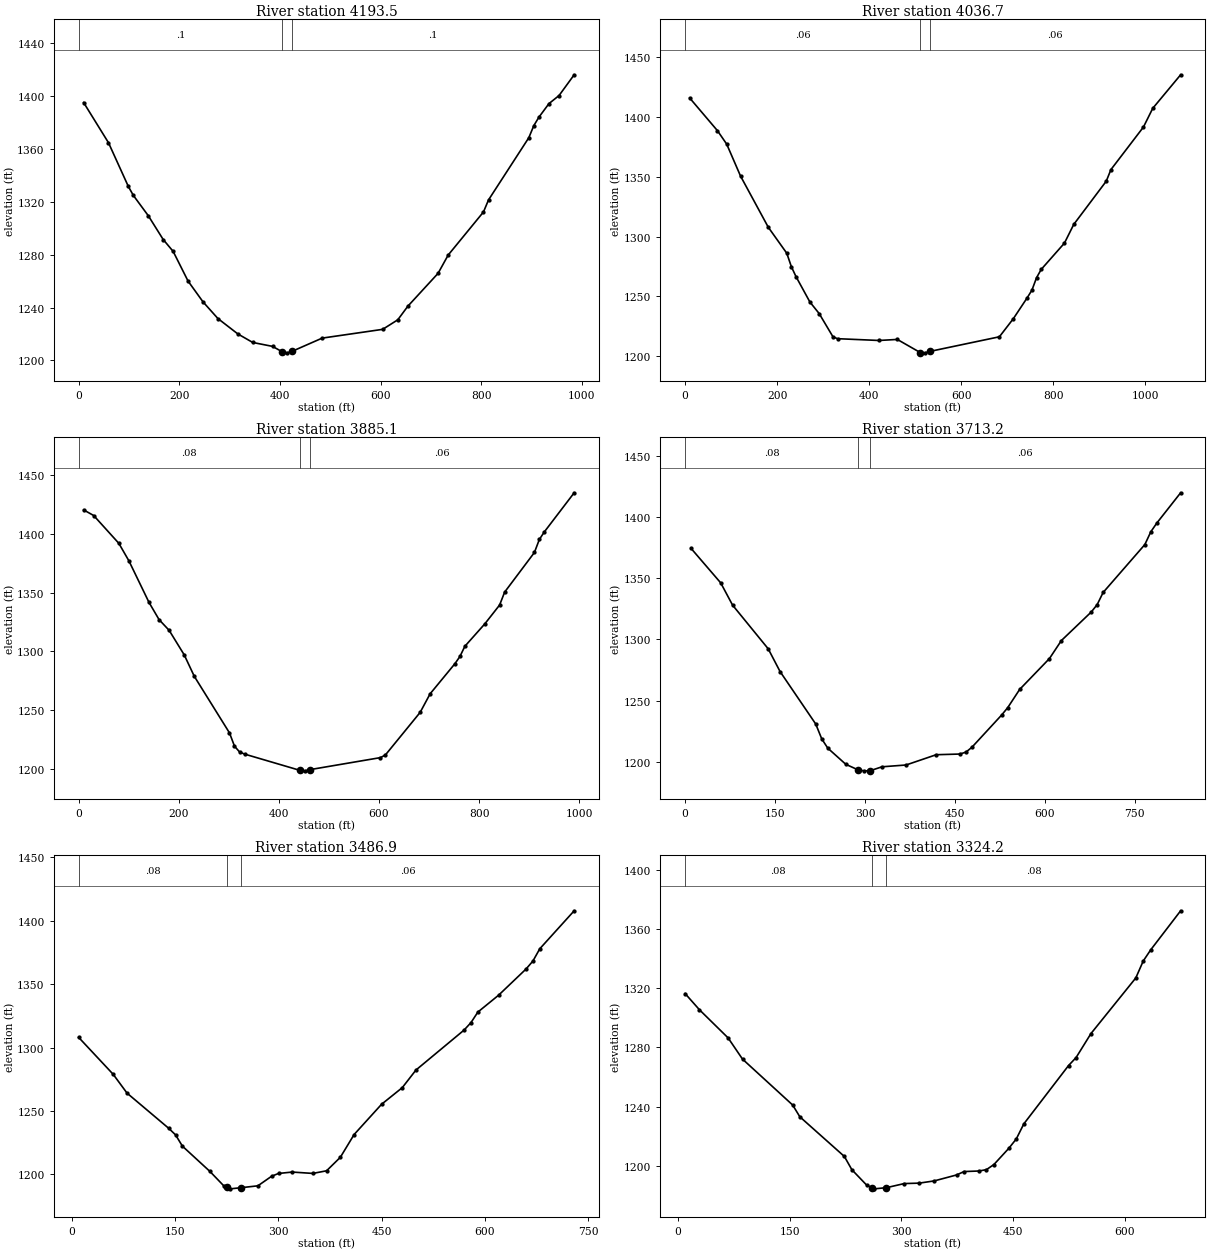
Type RM Length L Ch R = 1 ,4193.5  ,155,156.8,158.5
XS GIS Cut Line= 4
     1696791.263      224946.191     1696523.674       224711.72
     1696416.374      224724.967     1695971.276      224995.205
#Sta/Elev= 30
     9.9 1394.96    59.3 1364.59    98.8  1331.5   108.7 1324.76   138.4 1309.41
     168 1291.42   187.8 1282.44   217.4 1260.01   247.1  1244.3   276.7  1231.7
   316.3 1220.06   345.9 1213.61   385.3 1210.64   404.8 1206.48   414.8 1205.76
   424.8 1207.02   483.9 1216.89   604.1 1223.52   634.1 1230.72   654.2 1241.04
   714.2 1265.86   734.3 1279.69   804.4 1312.25   814.4 1321.33   894.5 1368.38
   904.5 1377.55   914.5 1383.86   934.5 1394.13   954.6 1400.26   984.6 1415.93
#Mann= 3 , 0 , 0
       0      .1       0   404.8    .045       0   424.8      .1       0
Bank Sta=404.8,424.8
XS Rating Curve= 0 ,0
Exp/Cntr=0.3,0.1

Type RM Length L Ch R = 1 ,4036.7  ,150.9,151.6,152.3
XS GIS Cut Line= 5
     1696857.445      224241.735     1696612.377      224433.816
     1696515.674      224560.987     1696364.659      224568.935
     1695932.808      224427.193
#Sta/Elev= 30
      10 1415.58    70.3 1388.33    90.4 1377.12   120.5 1350.44   180.8 1307.73
     221 1286.06     231 1274.78   241.1 1266.51   271.2 1245.39   291.3 1235.77
   321.4 1216.32   331.3 1214.78   421.2 1213.29   461.2 1214.15   511.5 1203.11
   521.5 1202.97   531.5 1204.13     683 1216.36   713.3 1231.45   743.6    1249
   753.7 1255.25   763.8 1265.68   773.9 1272.58   824.4 1294.53   844.6 1310.11
   915.3 1346.22   925.4 1355.85   996.1 1391.37  1016.3 1406.98  1076.9 1434.96
#Mann= 3 , 0 , 0
       0     .06       0   511.5    .045       0   531.5     .06       0
Bank Sta=511.5,531.5
XS Rating Curve= 0 ,0
Exp/Cntr=0.3,0.1

Type RM Length L Ch R = 1 ,3885.1  ,180.8,172,163.1
XS GIS Cut Line= 4
     1696853.523      224221.583     1696604.481      224408.365
     1696352.788      224414.988     1695926.236      224411.014
#Sta/Elev= 30
      10 1420.51    30.1 1415.72    80.3 1392.02   100.4 1377.09   140.6 1341.61
   160.7 1326.95   180.8 1317.83   210.9 1296.91     231 1278.64   301.3  1230.4
   311.3 1219.08   321.4 1214.17   331.4 1212.34   442.3 1198.43   452.3 1198.06
   462.3 1199.11   602.8 1209.33   612.7  1211.6   682.1 1247.91     702 1263.74
   751.6 1289.45   761.5 1295.54   771.4 1304.25   811.1 1323.29   840.8 1339.43
   850.8 1350.41   910.3 1384.24   920.2 1395.37   930.1 1401.77   989.7 1435.12
#Mann= 3 , 0 , 0
       0     .08       0   442.3    .045       0   462.3     .06       0
Bank Sta=442.3,462.3
XS Rating Curve= 0 ,0
Exp/Cntr=0.3,0.1

Type RM Length L Ch R = 1 ,3713.2  ,227.7,226.2,224.7
XS GIS Cut Line= 4
     1696721.495       224122.01     1696532.506      224208.556
      1696336.45      224286.272     1695937.276      224369.286
#Sta/Elev= 30
     9.9 1374.34    59.4 1346.13    79.2 1327.94   138.6 1292.26   158.4 1273.66
   217.9 1230.78   227.9 1218.66     238 1211.05   268.1 1197.85   288.2 1193.39
   298.2 1192.53   308.2 1192.56   328.4 1195.83   368.5  1197.3   418.8  1205.7
   458.5 1206.26   468.5 1207.85   478.4 1211.81   528.1 1238.22   538.1 1244.18
     558 1259.05   607.7 1284.29   627.6    1299   677.3 1322.26   687.3 1328.36
   697.2 1338.27   766.8 1377.43   776.8  1387.9   786.7 1394.97   826.5 1419.75
#Mann= 3 , 0 , 0
       0     .08       0   288.2    .045       0   308.2     .06       0
Bank Sta=288.2,308.2
XS Rating Curve= 0 ,0
Exp/Cntr=0.3,0.1

Type RM Length L Ch R = 1 ,3486.9  ,151,162.7,174.4
XS GIS Cut Line= 4
     1696562.532      223957.747     1696419.465      224005.436
     1696256.969      224081.386     1695946.107      224332.195
#Sta/Elev= 30
    10.1 1308.09    60.3 1278.94    80.4 1264.12   140.8 1236.44   150.8 1231.24
   160.8 1222.32   200.6 1202.46   220.6 1191.18  225.76 1189.87   230.5 1188.67
  245.64 1189.55   270.4 1191.06   290.3  1198.6   300.3 1200.79   320.2  1201.9
   350.1 1200.83   370.1  1202.9   390.1 1213.54   410.1  1231.5     450 1255.36
     480 1268.44   499.9 1282.34   569.8 1313.86   579.8 1319.75   589.8 1328.04
   619.8  1341.3   659.7 1361.96   669.7 1368.25   679.7 1377.95   729.6 1407.88
#Mann= 3 , 0 , 0
    10.1     .08       0  225.76    .045       0  245.64     .06       0
Bank Sta=225.76,245.64
XS Rating Curve= 0 ,0
Exp/Cntr=0.3,0.1

Type RM Length L Ch R = 1 ,3324.2  ,199,193.3,187.6
XS GIS Cut Line= 4
     1696562.532      223881.798     1696389.438      223890.629
     1696198.682      223885.331     1695909.015      223998.371
#Sta/Elev= 30
     9.6 1316.39    28.9 1305.41    67.4 1286.38    86.7 1272.07   154.1 1241.01
   163.7 1233.07   223.5 1206.26   233.6 1197.28   253.7 1186.75  260.12 1185.25
   263.7 1184.37  280.05 1185.16   303.9 1187.93     324 1188.23   344.1 1189.72
   374.2 1193.76   384.2 1196.05   404.3 1196.43   414.3 1197.35   424.3 1200.79
   444.4 1211.79   454.4 1218.12   464.5 1228.28   524.6 1267.74   534.7 1273.12
   554.7 1289.36   614.9 1326.95   624.9 1338.42     635    1346   675.1 1372.34
#Mann= 3 , 0 , 0
     9.6     .08       0  260.12    .045       0  280.05     .08       0
Bank Sta=260.12,280.05
XS Rating Curve= 0 ,0
Exp/Cntr=0.3,0.1

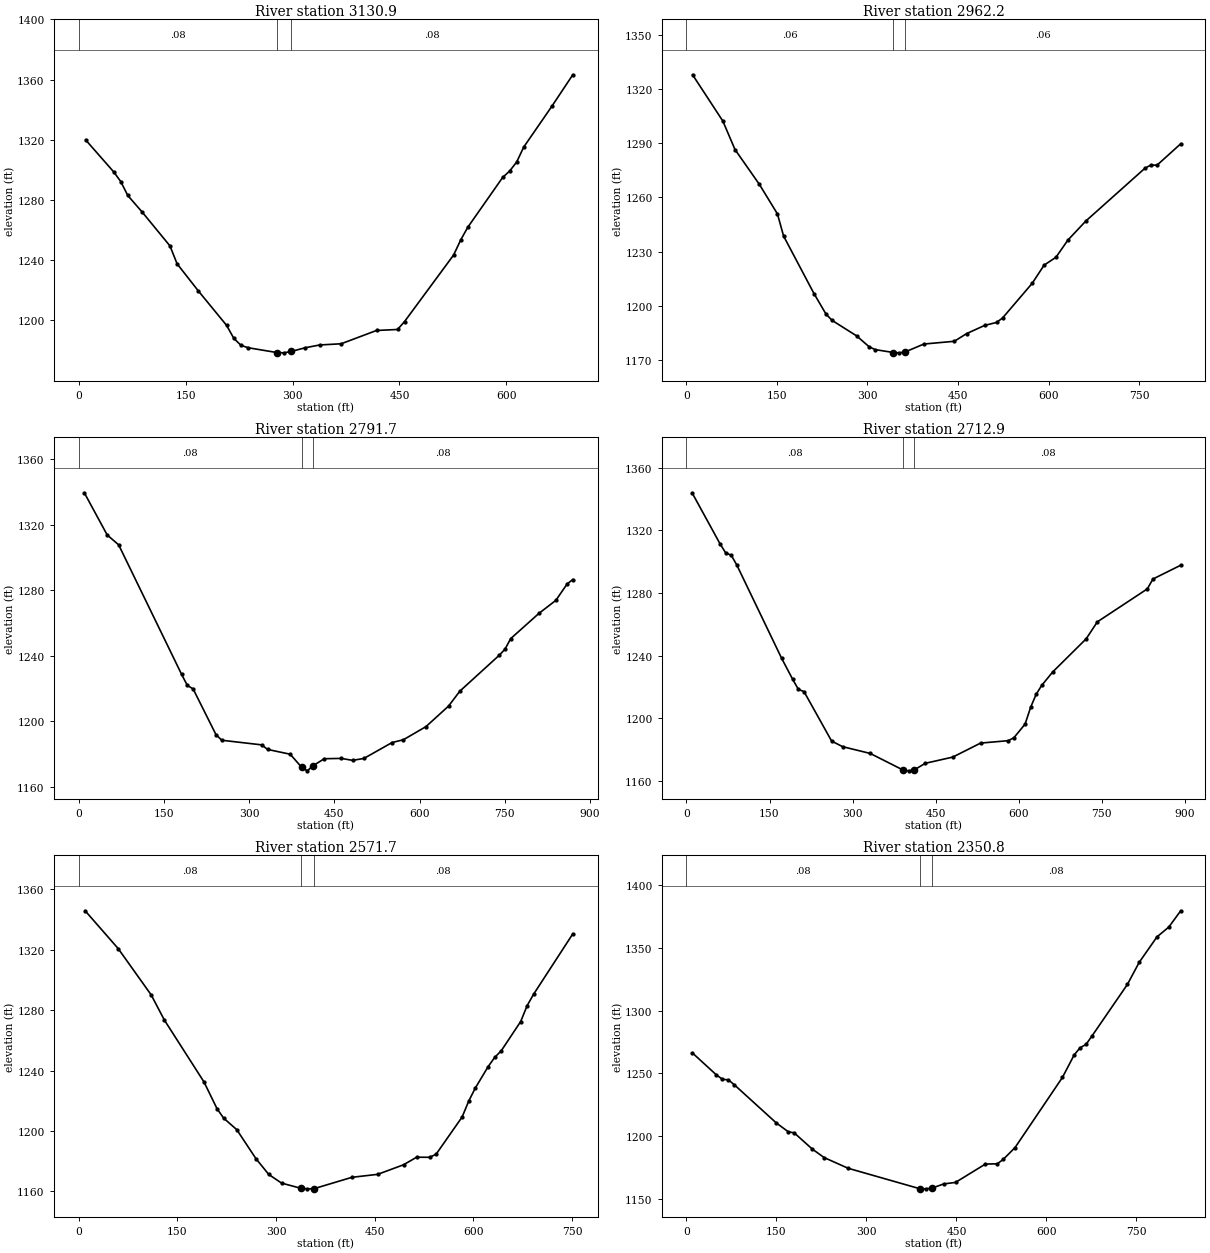
Type RM Length L Ch R = 1 ,3130.9  ,166.6,168.8,170.9
XS GIS Cut Line= 4
     1696527.207      223696.341     1696350.581      223678.678
     1696145.694      223728.133     1695882.521      223881.798
#Sta/Elev= 30
     9.9 1319.96    49.3  1298.7    59.2 1292.26      69 1283.02    88.8 1272.24
   128.2 1249.51   138.1 1237.68   167.6 1219.83   207.6 1196.71   217.7  1188.1
   227.7 1183.48   237.7 1181.89   277.9  1178.7   287.9 1178.49   297.9 1179.39
     318 1181.89   338.1 1183.72   368.2 1184.51   417.8 1193.35   447.3 1194.01
   457.1 1199.28   525.9 1243.49   535.7 1253.35   545.6 1261.81   594.7 1295.04
   604.6 1299.34   614.4 1305.34   624.2  1315.2   663.5 1342.19     693 1363.22
#Mann= 3 , 0 , 0
       0     .08       0   277.9    .045       0   297.9     .08       0
Bank Sta=277.9,297.9
XS Rating Curve= 0 ,0
Exp/Cntr=0.3,0.1

Type RM Length L Ch R = 1 ,2962.2  ,185.1,170.5,155.8
XS GIS Cut Line= 4
     1696523.674      223593.898     1696341.749      223535.611
     1696050.316       223569.17     1695760.649      223736.965
#Sta/Elev= 30
    10.1 1327.89    60.3 1302.25    80.4 1286.49   120.7 1267.26   150.8 1250.82
   160.9 1238.61   211.3 1206.74   231.5 1195.22   241.6 1191.82   282.1 1183.27
   302.3 1177.39   312.4 1175.72   342.9 1174.09   352.9 1173.91   362.9 1174.47
   393.4 1178.78   443.9 1180.31   464.2 1184.54   494.2  1189.1   513.9 1190.74
   523.8 1193.19     573 1212.42   592.7 1222.47   612.4 1226.85   632.1 1236.33
   661.6 1246.82   760.1 1276.22   769.9 1277.92   779.8  1277.8   819.1 1289.67
#Mann= 3 , 0 , 0
       0     .06       0   342.9    .045       0   362.9     .06       0
Bank Sta=342.9,362.9
XS Rating Curve= 0 ,0
Exp/Cntr=0.3,0.1

Type RM Length L Ch R = 1 ,2791.7  ,73.8,78.8,84.1
XS GIS Cut Line= 4
     1696394.145      223101.859     1696176.895      223353.551
     1696077.543      223437.007     1695771.538       223705.92
#Sta/Elev= 30
    10.1 1339.38    50.4 1313.64    70.5 1307.66   181.4 1228.57   191.4 1221.89
   201.5 1219.81   241.8 1191.88   251.9 1188.47   322.4 1185.64   332.5 1182.87
   372.4 1179.94   392.4 1172.03   402.4 1169.81   412.4 1172.88   432.3  1177.2
   462.2 1177.39   482.1 1176.21     502 1177.36   551.7 1187.09   571.5 1188.76
   611.3 1196.79     651  1209.3   670.9 1218.41   740.4 1240.36   750.4 1244.05
   760.3 1250.43     810 1265.82   839.8 1273.78   859.7  1283.8   869.6 1286.47
#Mann= 3 , 0 , 0
       0     .08       0   392.4    .045       0   412.4     .08       0
Bank Sta=392.4,412.4
XS Rating Curve= 0 ,0
Exp/Cntr=0.3,0.1

Type RM Length L Ch R = 1 ,2712.9  ,151.1,141.2,131
XS GIS Cut Line= 4
     1696385.906      223094.046     1696232.241      223254.776
     1696003.277      223375.367     1695750.052      223699.873
#Sta/Elev= 30
    10.1 1343.88    60.6 1311.34    70.8 1305.56    80.9 1304.04      91 1297.75
   171.8 1238.38     192 1224.82   202.2 1218.49   212.3  1217.1   262.2 1185.54
   282.1 1181.96   331.9 1177.65   391.5 1167.02   401.5 1166.55   411.5 1167.17
   431.4 1171.35   481.1 1175.32   531.3 1184.25   581.5 1185.79   591.6 1187.72
   611.7 1196.36   621.7 1207.06   631.7 1215.36   641.8  1221.1   661.9 1229.72
   722.1 1250.77   742.2 1261.56   832.5 1282.59   842.6 1288.87   892.8 1297.67
#Mann= 3 , 0 , 0
       0     .08       0   391.5    .045       0   411.5     .08       0
Bank Sta=391.5,411.5
XS Rating Curve= 0 ,0
Exp/Cntr=0.3,0.1

Type RM Length L Ch R = 1 ,2571.7  ,219.6,220.9,222.2
XS GIS Cut Line= 4
     1696290.528      223021.629     1696085.641      223127.605
     1695939.042       223309.53     1695707.662      223479.091
#Sta/Elev= 30
      10 1345.86    60.2 1320.83   110.3 1290.19   130.4 1273.49   190.6  1232.5
   210.6 1214.65   220.6 1208.46   240.4 1200.91   269.6 1181.68   289.1  1171.2
   308.6 1165.47   337.5 1162.09   347.5 1161.68   357.5 1161.74   415.6 1169.33
   454.6 1171.27     494 1177.63   513.8 1182.64   533.6 1182.57   543.4 1184.59
     583 1209.27   592.9 1219.68   602.8 1228.28   622.6 1242.67   632.5 1248.74
   642.4 1253.09     672 1272.51   681.9  1283.1   691.8 1290.69   751.2 1330.56
#Mann= 3 , 0 , 0
       0     .08       0   337.5    .045       0   357.5     .08       0
Bank Sta=337.5,357.5
XS Rating Curve= 0 ,0
Exp/Cntr=0.3,0.1

Type RM Length L Ch R = 1 ,2350.8  ,308,309.3,310.6
XS GIS Cut Line= 4
     1696013.225      222744.326     1695905.483      223012.798
     1695758.883      223175.294     1695552.231      223413.739
#Sta/Elev= 30
      10 1266.18    49.9 1248.72    59.9 1245.26    69.8 1244.78    79.8 1240.85
   149.6 1210.52   169.6 1203.46   179.6 1202.56   209.5 1189.74   229.4 1182.91
   269.3  1174.4   388.7 1158.11   398.7    1158   408.7 1158.48   428.6 1161.89
   448.4 1163.12   498.2 1177.74     518 1177.92   527.9 1181.42   547.6 1190.86
   626.5 1246.67   646.2 1264.67     656 1270.35   665.9 1273.03   675.8  1279.7
   734.9 1320.81   754.6 1338.44   784.2 1358.68   803.9 1366.47   823.7 1379.44
#Mann= 3 , 0 , 0
       0     .08       0   388.7    .045       0   408.7     .08       0
Bank Sta=388.7,408.7
XS Rating Curve= 0 ,0
Exp/Cntr=0.3,0.1

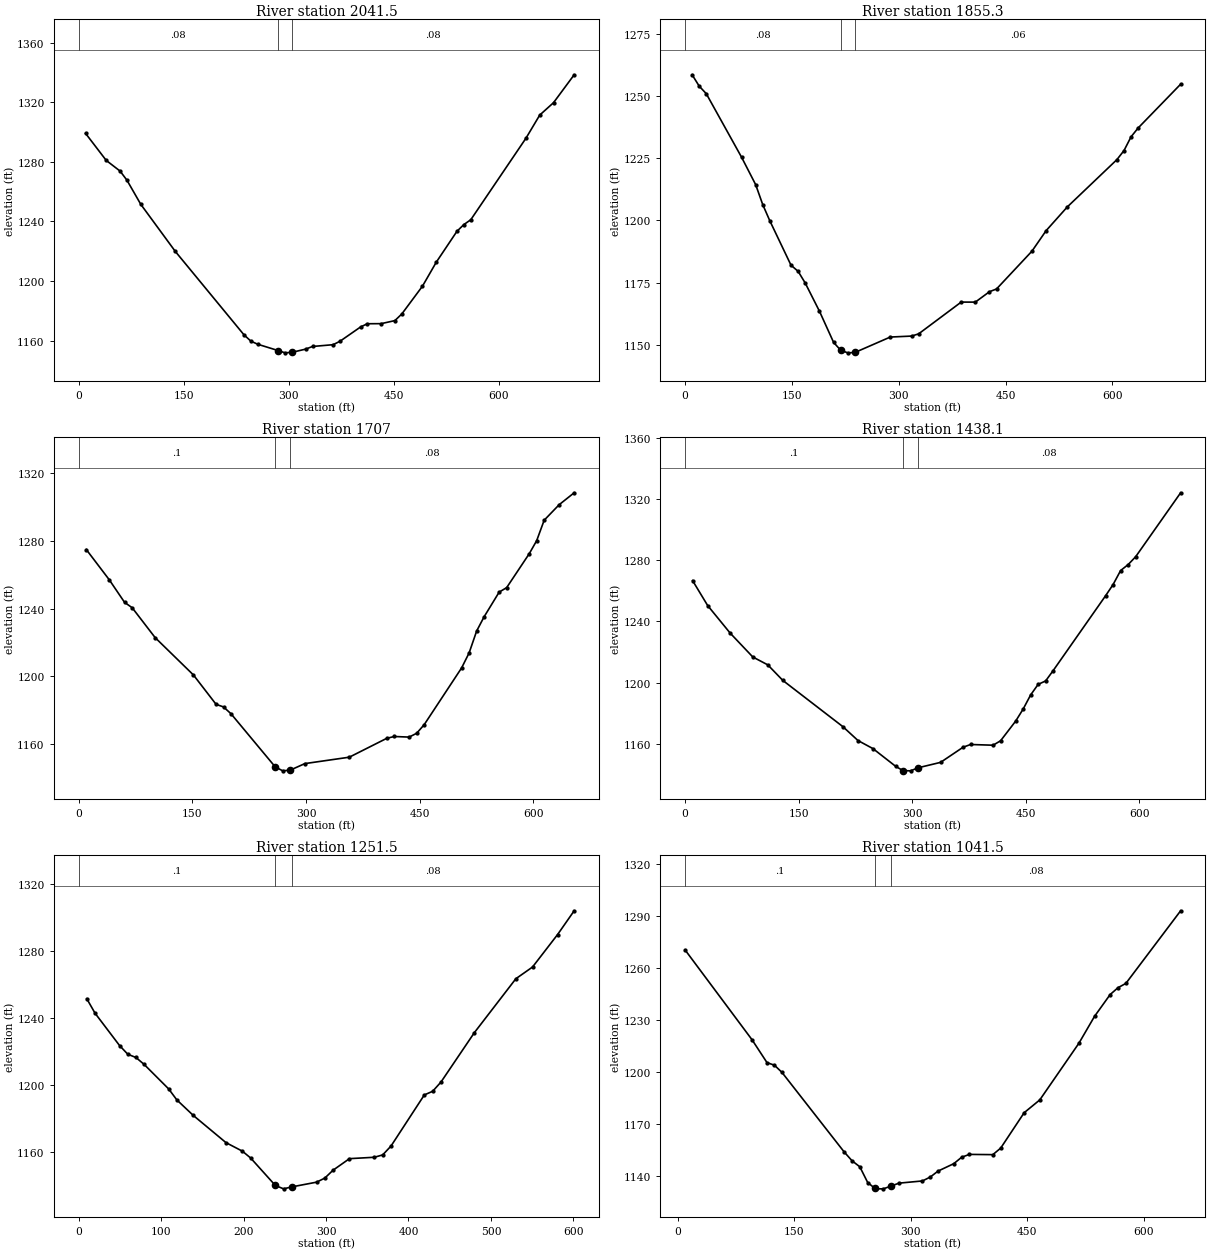
Type RM Length L Ch R = 1 ,2041.5  ,184.8,186.2,187.7
XS GIS Cut Line= 4
     1695829.533      222645.415     1695718.259       222770.82
     1695545.165      222943.914     1695407.397       223205.32
#Sta/Elev= 30
     9.9 1299.04    39.4 1280.91    59.2 1273.74      69 1267.64    88.8 1251.42
   138.1 1219.84   236.2 1163.89     246 1159.67   255.8 1157.57   284.9 1153.34
   294.9  1151.8   304.9 1152.16   324.3 1154.29   334.1 1156.07   363.5 1157.26
   373.3 1159.55   402.7 1169.14   412.4 1171.32   432.1 1171.38   451.8 1173.43
   461.7 1177.89   491.2 1196.54   510.9 1212.61   540.5 1233.38   550.3 1237.85
   560.2 1241.09     639 1295.77   658.7 1311.31   678.4 1319.63   707.9 1338.35
#Mann= 3 , 0 , 0
       0     .08       0   284.9    .045       0   304.9     .08       0
Bank Sta=284.9,304.9
XS Rating Curve= 0 ,0
Exp/Cntr=0.3,0.1

Type RM Length L Ch R = 1 ,1855.3  ,156.1,148.3,140.5
XS GIS Cut Line= 4
     1695691.765      222557.102     1695589.322      222650.714
      1695410.93      222809.678     1695227.239      223069.318
#Sta/Elev= 30
     9.9 1258.55    19.8 1253.98    29.7 1250.96    79.3  1225.4    99.1 1214.37
     109 1206.36   118.9 1199.88   148.7 1181.99   158.7 1179.52   168.6 1174.85
   188.6 1163.52   208.5 1150.96   218.4 1147.81   228.4 1146.75   238.4 1146.89
   288.1  1153.1     318 1153.49   327.9 1154.38   387.7 1167.16   407.5 1167.14
   427.4 1171.34   437.3 1172.43     487 1187.62   506.9 1195.87   536.7 1205.43
   606.3 1224.43   616.3 1228.09   626.2 1233.62   636.1 1237.15   695.8 1254.76
#Mann= 3 , 0 , 0
       0     .08       0   218.4    .045       0   238.4     .06       0
Bank Sta=218.4,238.4
XS Rating Curve= 0 ,0
Exp/Cntr=0.3,0.1

Type RM Length L Ch R = 1 ,1707    ,266.6,268.8,271.1
XS GIS Cut Line= 4
     1695557.529      222398.139     1695455.086      222535.907
     1695350.877      222712.533     1695153.056      222906.822
#Sta/Elev= 30
    10.1 1274.83    40.4 1257.02    60.6 1243.71    70.7 1240.51     101  1222.9
   151.5  1200.9   181.4 1183.59   191.2 1182.06     201 1178.08   259.3  1146.8
   269.3 1144.39   279.3 1144.81   298.6 1148.66   357.2 1152.43   406.5 1163.52
   416.4 1164.63   436.2 1164.28   446.1 1166.53     456 1171.56   505.5 1205.09
   515.4 1213.95   525.3 1226.81   535.2 1235.24     555 1249.73   564.9 1252.38
   594.6 1272.29   604.5 1280.04   614.4  1292.1   634.2 1301.26     654 1308.28
#Mann= 3 , 0 , 0
       0      .1       0   259.3    .045       0   279.3     .08       0
Bank Sta=259.3,279.3
XS Rating Curve= 0 ,0
Exp/Cntr=0.3,0.1

Type RM Length L Ch R = 1 ,1438.1  ,185.8,186.7,187.6
XS GIS Cut Line= 4
     1695373.838      222258.604     1695234.304      222399.905
     1695130.094      222544.739     1694969.365       222770.82
#Sta/Elev= 30
     9.9 1266.75    29.8 1250.42    59.6 1232.33    89.4 1216.74   109.2 1211.58
   129.1 1201.38   208.5 1171.06   228.3 1162.03   248.1 1156.73   277.9  1145.2
   287.7 1142.31   297.7 1142.18   307.7 1144.18   337.4 1147.73   367.1 1157.64
     377 1159.43   406.7 1158.96   416.6 1161.86   436.5 1174.72   446.4 1182.61
   456.3 1191.87   466.2  1198.8   476.1 1201.05     486 1207.78   555.3 1256.85
   565.2 1264.17   575.1 1273.32   585.1 1277.26     595 1282.39   654.4 1324.27
#Mann= 3 , 0 , 0
       0      .1       0   287.7    .045       0   307.7     .08       0
Bank Sta=287.7,307.7
XS Rating Curve= 0 ,0
Exp/Cntr=0.3,0.1

Type RM Length L Ch R = 1 ,1251.5  ,213.5,210,206.4
XS GIS Cut Line= 4
      1695207.81      222168.525     1695077.106      222304.527
     1694985.261      222422.867      1694858.09      222652.481
#Sta/Elev= 30
     9.9 1251.25    19.9 1242.62    49.6 1223.33    59.6 1218.13    69.5 1216.18
    79.4 1212.07   109.2 1197.41   119.1 1190.86     139 1181.61   178.7 1165.35
   198.6 1160.25   208.6 1156.17   238.5 1139.81   248.5 1137.77   258.5 1138.94
   288.5 1141.75   298.5 1144.18   308.5 1148.89   328.4 1155.79   358.6 1156.62
   368.7 1158.03   378.8 1163.32   419.2 1193.84   429.3 1196.01   439.4 1201.53
   479.8 1230.97   530.2 1263.21   550.4 1270.19   580.7 1289.52   600.9 1303.77
#Mann= 3 , 0 , 0
       0      .1       0   238.5    .045       0   258.5     .08       0
Bank Sta=238.5,258.5
XS Rating Curve= 0 ,0
Exp/Cntr=0.3,0.1

Type RM Length L Ch R = 1 ,1041.5  ,242.9,244.9,246.9
XS GIS Cut Line= 4
     1695027.651      221997.198     1694941.104      222112.005
     1694845.726      222278.033     1694713.257      222560.635
#Sta/Elev= 30
     9.6 1270.49    95.8  1218.6     115 1205.43   124.6 1203.92   134.2 1199.82
   214.3 1153.85   224.4 1148.76   234.5 1145.24   244.6 1136.18  253.63 1132.88
   254.6 1132.52   264.7 1132.52   274.7 1134.12   284.9 1135.81   315.1 1137.08
   325.2 1139.35   335.2 1142.78   355.4 1147.05   365.5 1150.76   375.5 1152.41
   405.7 1152.27   415.8 1156.05     446 1176.49   466.1 1183.88   516.5 1216.64
   536.6 1232.16   556.7 1244.75   566.8  1248.7   576.9 1251.17   647.4 1293.12
#Mann= 3 , 0 , 0
     9.6      .1       0  253.63    .045       0   274.7     .08       0
Bank Sta=253.63,274.7
XS Rating Curve= 0 ,0
Exp/Cntr=0.3,0.1

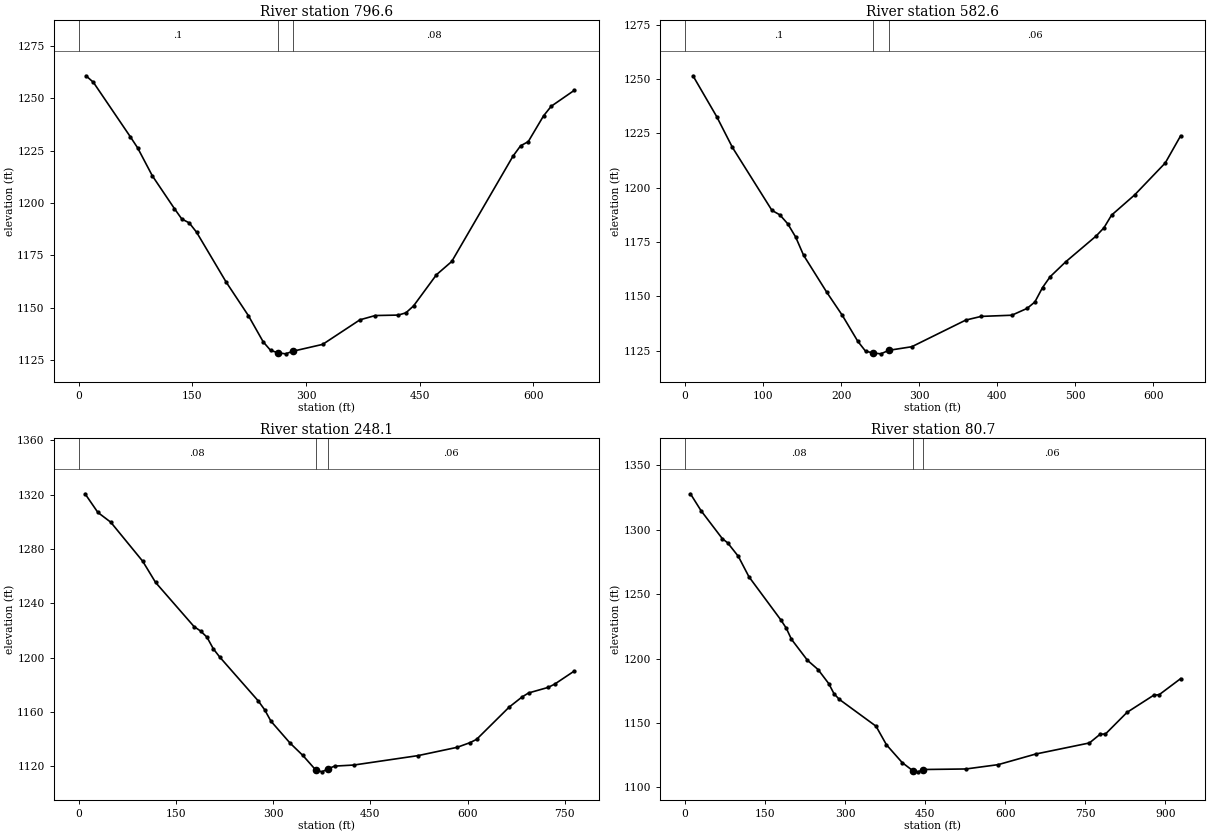
Type RM Length L Ch R = 1 ,796.6   ,212.8,214,215.2
XS GIS Cut Line= 4
     1694847.493      221862.962     1694723.854      222013.094
     1694630.242      222150.862     1694554.293      222433.464
#Sta/Elev= 30
     9.7 1260.74    19.4 1257.65    68.1 1231.65    77.8 1226.32    97.2 1212.96
   126.4 1197.25   136.1 1192.31   145.9 1190.45   155.6 1185.98   194.5 1162.23
   223.9 1146.15   243.5  1133.6   253.3 1129.51   262.9  1128.4   272.9 1127.88
   282.9 1129.15   321.9  1132.4   371.1 1144.14   391.3 1146.18   421.6  1146.4
   431.7 1147.47   441.8 1150.77     472 1165.67   492.2 1172.01     573 1222.34
     583 1227.28   593.1 1229.26   613.3 1241.59   623.4 1246.17   653.7 1253.75
#Mann= 3 , 0 , 0
       0      .1       0   262.9    .045       0   282.9     .08       0
Bank Sta=262.9,282.9
XS Rating Curve= 0 ,0
Exp/Cntr=0.3,0.1

Type RM Length L Ch R = 1 ,582.6   ,325.1,334.6,344.1
XS GIS Cut Line= 4
     1694660.269      221758.752     1694557.826      221884.157
     1694444.785      222034.289     1694208.106      222193.253
#Sta/Elev= 30
    10.1 1251.47    40.5 1232.69    60.7 1218.49   111.3 1189.56   121.4 1187.51
   131.6 1183.37   141.7 1177.29   151.8 1168.95   181.7 1151.82   201.5 1141.27
   221.3 1129.36   231.2 1124.83   240.9 1123.98   250.9 1123.59   260.9  1125.2
   290.5 1126.86   359.7 1139.12   379.4 1140.81   418.7 1141.35   438.3  1144.5
   448.2 1147.43     458 1154.06   467.8 1159.06   487.5 1165.84   526.8 1177.81
   536.7 1181.55   546.5 1187.39     576 1196.66   615.3 1211.38     635 1223.87
#Mann= 3 , 0 , 0
       0      .1       0   240.9    .045       0   260.9     .06       0
Bank Sta=240.9,260.9
XS Rating Curve= 0 ,0
Exp/Cntr=0.3,0.1

Type RM Length L Ch R = 1 ,248.1   ,149.7,167.4,168.4
XS GIS Cut Line= 4
     1694554.293      221513.242     1694328.212      221689.868
     1694160.417      221792.311     1694128.624      222071.381
#Sta/Elev= 30
     9.9 1320.71    29.7 1306.95    49.5 1299.79    98.9 1270.96   118.7 1255.37
   178.1 1222.81     188 1219.61   197.9 1215.08   207.8 1206.43   217.6 1200.42
     277  1168.1   286.9 1161.59   296.7 1153.09   326.2 1136.95   345.9 1127.86
   365.4 1117.35   375.4 1115.79   385.4  1118.2     395 1120.02   424.5  1120.8
   523.6 1127.75   583.8 1133.85   603.9 1137.33   613.9 1139.74   664.1 1163.49
   684.1    1171   694.1 1173.92   724.2 1178.01   734.3 1180.42   764.4 1190.02
#Mann= 3 , 0 , 0
       0     .08       0   365.4    .045       0   385.4     .06       0
Bank Sta=365.4,385.4
XS Rating Curve= 0 ,0
Exp/Cntr=0.3,0.1

Type RM Length L Ch R = 1 ,80.7    ,97.7,80.7,80.3
XS GIS Cut Line= 5
     1694548.994      221484.982     1694316.132      221638.805
     1694178.654      221585.714     1694126.582      221614.623
     1694114.908      222056.864
#Sta/Elev= 30
      10 1327.96    29.9 1314.82    69.8 1293.09    79.7 1289.89    99.7 1279.39
   119.6 1263.52   179.4    1230   189.4  1223.7   199.3 1214.96   229.2 1198.69
   249.2 1191.44   269.1 1180.58   279.1 1172.63   288.9 1168.33   357.7 1147.49
   377.3 1133.02   406.8  1119.2   426.4 1113.01   436.4 1112.05   446.4 1113.86
   526.2 1114.28   586.6 1117.64   656.9 1125.88   757.5 1134.48   777.6 1141.25
   787.6 1141.44   827.9 1158.21   878.1 1171.58   888.2 1171.94   928.4 1184.42
#Mann= 3 , 0 , 0
       0     .08       0   426.4    .045       0   446.4     .06       0
Bank Sta=426.4,446.4
XS Rating Curve= 0 ,0
Exp/Cntr=0.3,0.1

Chan Stop Cuts=-1
Use User Specified Reach Order=0